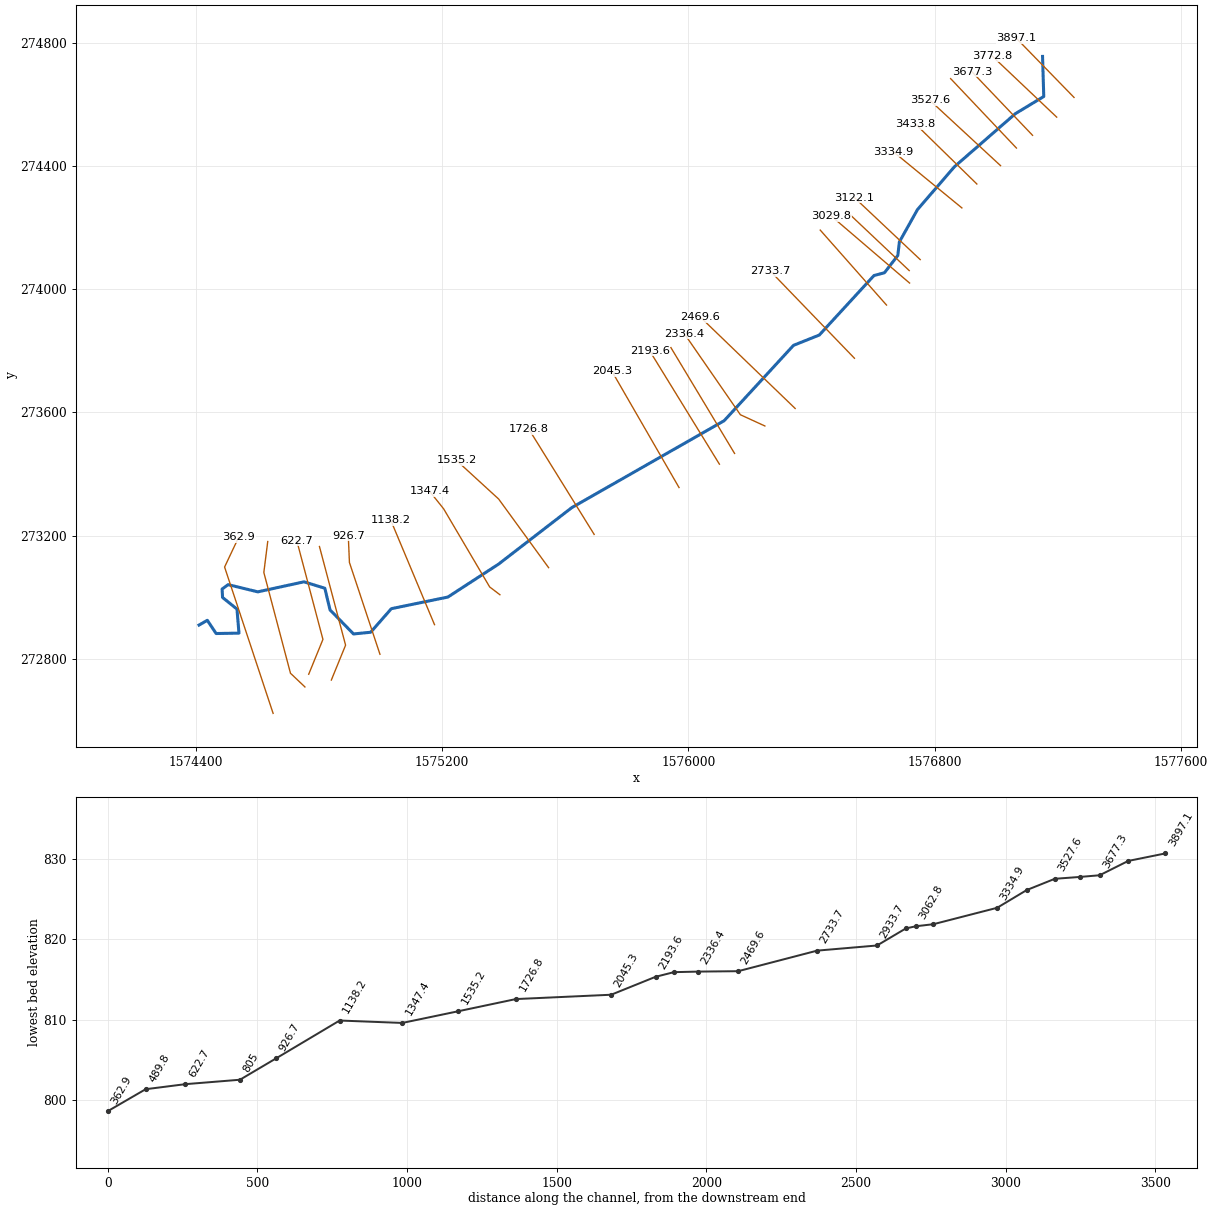
--- LEASONRN.prj (project) ---

Proj Title=LEASONRN
Current Plan=p01
Geom File=g01
Flow File=f01
Plan File=p01
DSS Export Rating Curves=0
DSS Export Rating Curve Sorted=0
DSS Export Volume Flow Curves=0
DXF OffsetX=0
DXF OffsetY=0
DXF ScaleX=0
DXF ScaleY=0

--- LEASONRN.p01 (plan) ---

Plan Title=Floodplain
Program Version=4.00
Geom File=g01
Flow File=f01
K Sum by GR=0
Std Step Tol=0.01
Critical Tol=0.01
Num of Std Step Trials=20
Max Error Tol=0.3
Flow Tol Ratio=0.001
Split Flow NTrial=30
Split Flow Tol=0.02
Split Flow Ratio=0.02
Log Output Level=0
Friction Slope Method=1
Unsteady Friction Slope Method=2
Unsteady Bridges Friction Slope Method=1
Global Log Level=0
CheckData=False
Run HTab=0
Run UNet=0
Run PostProcess=0
UNET Theta=0
UNET Theta Warmup=0
UNET ZTol=0
UNET ZSATol=0
UNET MxIter=0
UNET MaxInSteps=0
UNET DtIC=0
UNET DtMin=0
UNET MaxCRTS=0
UNET WFStab=0
UNET SFStab=0
UNET WFX=0
UNET SFX=0
UNET DSS MLevel=0
UNET DZMax Abort=0
UNET Convert EG Bridges=0
UNET Use Existing IB Tables=0
UNET Froude Limit=0
UNET Froude Power=0
Write IC File=0
Echo Input=False
Echo Output=False
Write Detailed=0

--- LEASONRN.f01 (steady flow) ---

Flow Title=NFF Regression Equation
Program Version=4.10
Number of Profiles= 1
Profile Names=P100yr
River Rch & RM=LEASONRN,Main            ,3897.1
749.9183
River Rch & RM=LEASONRN,Main            ,805
806.0787
River Rch & RM=LEASONRN,Main            ,489.8
807.0602
Boundary for River Rch & Prof#=LEASONRN,Main            , 1
Up Type= 0
Dn Type= 3
Dn Slope=0.01432
DSS Import GetInterval= 0
DSS Import GetPeak= 0
DSS Import FillOption= 0

--- LEASONRN.g01 (geometry) ---

Geom Title=USGS 10m DEM
Program Version=4.10

River Reach=LEASONRN        ,Main
Reach XY= 30
     1577149.827      274756.099     1577153.731      274625.954
     1577061.328      274569.991     1576863.506      274397.678
      1576743.65      274258.714     1576684.824       274153.56
      1576679.79      274109.636     1576636.387       274053.56
     1576602.404      274044.527     1576424.755      273851.216
      1576340.97      273817.748     1576115.818      273573.074
     1575621.306      273291.019     1575383.104      273107.286
     1575218.593      273000.432     1575035.087       272962.69
     1574967.988      272886.151     1574912.258      272880.595
     1574835.964      272958.785     1574819.045      273029.064
     1574751.369      273049.887     1574601.441      273017.351
     1574505.133      273040.777     1574485.611      273026.461
     1574486.913       272999.13     1574533.765      272961.388
     1574540.272      272883.301     1574466.089      272881.999
     1574437.457      272924.947     1574410.575      272909.478

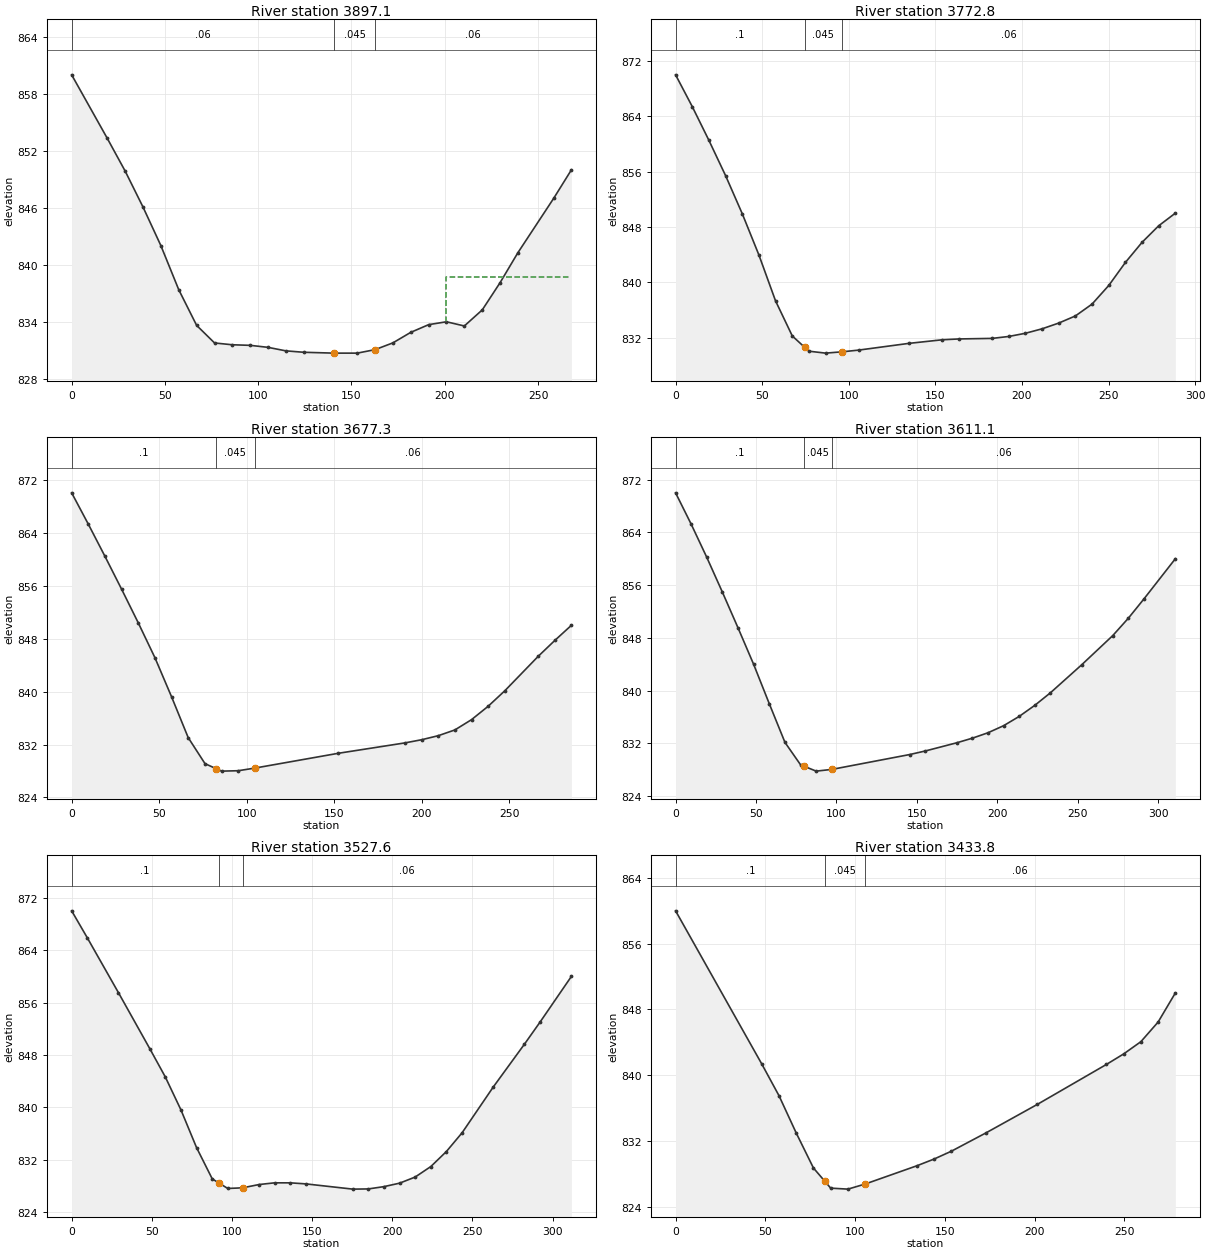
Type RM Length L Ch R = 1 ,3897.1  ,119.5,124.4,127.8
XS GIS Cut Line= 2
     1577252.002      274622.961     1577064.997      274814.821
#Sta/Elev= 26
       0     860    19.1  853.31    28.7  849.86    38.3  846.06    47.8  842.03
    57.4  837.38      67  833.62    76.6  831.77    86.1  831.58    95.7  831.52
   105.2  831.31   114.8  830.94   124.4  830.79   140.6   830.7   153.1   830.7
   162.7  831.07   172.2  831.78   181.8  832.89   191.4   833.7   200.9     834
   210.5  833.56   220.1  835.25   229.6   838.1   239.2  841.27   258.4     847
   267.9     850
#Mann= 3 , 0 , 0
       0     .06       0   140.6    .045       0   162.7     .06       0
#XS Ineff= 2 , 0
                          200.88          838.76
Permanent Ineff=
       F       F
Bank Sta=140.6,162.7
XS Rating Curve= 0 ,0
Exp/Cntr=0.3,0.1

Type RM Length L Ch R = 1 ,3772.8  ,96.7,95.4,94.2
XS GIS Cut Line= 2
      1577195.77      274558.909     1576986.257       274757.46
#Sta/Elev= 28
       0     870     9.6  865.42    19.2  860.55    28.9  855.41    38.5  849.92
    48.1  843.96    57.7  837.33    67.4  832.24    74.5  830.61      77  830.04
    86.6  829.76    96.2  829.95   105.8   830.2   134.7  831.17     154  831.69
   163.6  831.81   182.8  831.89   192.4  832.17     202  832.63   211.7  833.28
   221.3  834.11   230.9  835.14   240.5  836.85   250.2  839.56   259.8  842.89
   269.4  845.79     279  848.18   288.6     850
#Mann= 3 , 0 , 0
       0      .1       0    74.5    .045       0    96.2     .06       0
Bank Sta=74.5,96.2
XS Rating Curve= 0 ,0
Exp/Cntr=0.3,0.1

Type RM Length L Ch R = 1 ,3677.3  ,66.3,66.2,66.2
XS GIS Cut Line= 2
     1577117.354      274499.854     1576920.194      274706.545
#Sta/Elev= 24
       0     870     9.5  865.28      19  860.43    28.6  855.42    38.1  850.35
    47.6   845.1    57.1   839.2    66.6  833.04    76.2  829.11    82.4  828.37
    85.7  827.98    95.2  828.04   104.7  828.44   152.3  830.67   190.4  832.24
     200  832.72   209.5  833.33     219   834.2   228.5  835.75     238  837.77
   247.6  840.13   266.6  845.31   276.1  847.71   285.6     850
#Mann= 3 , 0 , 0
       0      .1       0    82.4    .045       0   104.7     .06       0
Bank Sta=82.4,104.7
XS Rating Curve= 0 ,0
Exp/Cntr=0.3,0.1

Type RM Length L Ch R = 1 ,3611.1  ,81.9,83.5,84.9
XS GIS Cut Line= 2
     1577064.997      274458.521     1576851.307      274684.017
#Sta/Elev= 26
       0     870     9.7  865.24    19.4  860.21    29.1  854.93    38.8  849.52
    48.5  843.99    58.2  838.03      68  832.13    77.7  828.73    79.8  828.52
    87.4  827.77    97.1  828.03   145.6  830.29   155.3  830.83   174.8  832.07
   184.5  832.77   194.2  833.59   203.9  834.66   213.6  836.07   223.3  837.75
     233  839.65   252.4  843.89   271.8  848.34   281.5  850.98   291.2  853.91
   310.7     860
#Mann= 3 , 0 , 0
       0      .1       0    79.8    .045       0    97.1     .06       0
Bank Sta=79.8,97.1
XS Rating Curve= 0 ,0
Exp/Cntr=0.3,0.1

Type RM Length L Ch R = 1 ,3527.6  ,94.4,93.8,93.2
XS GIS Cut Line= 2
     1577013.422       274401.43     1576784.492      274613.037
#Sta/Elev= 27
       0     870     9.7  865.91    29.2  857.51    48.7  848.99    58.4  844.67
    68.2  839.62    77.9  833.89    87.7  829.11    91.7   828.5    97.4  827.64
   106.7  827.74   116.9  828.24   126.6   828.5   136.4   828.5   146.1  828.34
   175.4  827.54   185.1  827.57   194.8  827.92   204.6  828.45   214.3  829.38
   224.1  830.99   233.8  833.28   243.6  836.14     263  843.11   282.5  849.66
   292.3  853.05   311.8     860
#Mann= 3 , 0 , 0
       0      .1       0    91.7    .045       0   106.7     .06       0
Bank Sta=91.7,106.7
XS Rating Curve= 0 ,0
Exp/Cntr=0.3,0.1

Type RM Length L Ch R = 1 ,3433.8  ,96.9,98.9,100.9
XS GIS Cut Line= 2
     1576936.476      274341.806     1576737.379      274536.405
#Sta/Elev= 19
       0     860      48  841.37    57.6  837.51    67.2  832.97    76.8  828.71
    83.2  827.08    86.4  826.26      96  826.14   105.6  826.76   134.4  828.98
     144   829.8   153.6  830.75   172.8  832.97   201.6  836.46     240  841.31
   249.6  842.59   259.2  844.08   268.8  846.47   278.4  850.01
#Mann= 3 , 0 , 0
       0      .1       0    83.2    .045       0   105.6     .06       0
Bank Sta=83.2,105.6
XS Rating Curve= 0 ,0
Exp/Cntr=0.3,0.1

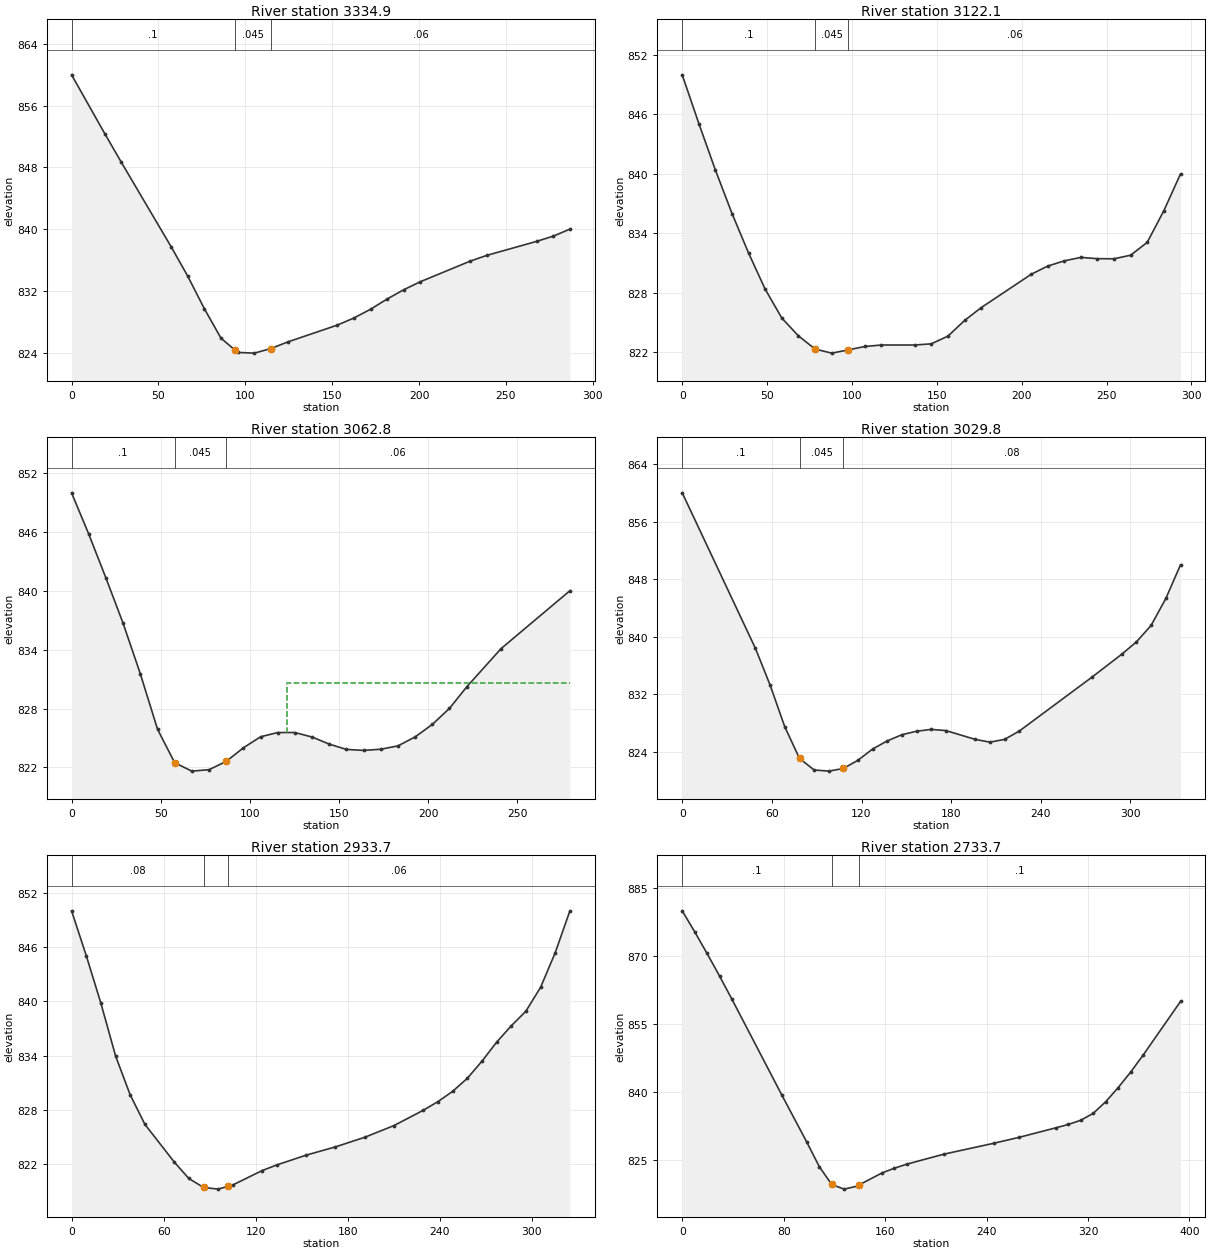
Type RM Length L Ch R = 1 ,3334.9  ,215.1,212.8,211.6
XS GIS Cut Line= 2
     1576887.833       274264.16     1576666.092      274446.008
#Sta/Elev= 23
       0     860    19.1  852.38    28.7  848.64    57.4  837.68    66.9  833.89
    76.5  829.65      86  825.87    93.9  824.35    95.6  824.02   105.2  823.93
   114.7  824.52   124.3  825.37   152.9  827.56   162.5  828.48   172.1  829.62
   181.6  830.94   191.2  832.15   200.7  833.18   229.4  835.85     239   836.6
   267.6  838.41   277.2  839.09   286.8     840
#Mann= 3 , 0 , 0
       0      .1       0    93.9    .045       0   114.7     .06       0
Bank Sta=93.9,114.7
XS Rating Curve= 0 ,0
Exp/Cntr=0.3,0.1

Type RM Length L Ch R = 1 ,3122.1  ,58.4,59.3,59.2
XS GIS Cut Line= 2
     1576752.506      274096.316     1576538.857      274297.656
#Sta/Elev= 28
       0     850     9.8  845.08    19.6  840.36    29.4  835.97    39.1     832
    48.9  828.34    58.7  825.43    68.5  823.63    78.3   822.3    88.1  821.89
    97.9  822.22   107.6  822.56   117.4  822.71     137  822.71   146.8  822.83
   156.6  823.61   166.4  825.19   176.1  826.48   205.5  829.84   215.3  830.68
   225.1  831.21   234.9  831.56   244.6  831.43   254.4  831.42   264.2  831.78
     274  833.08   283.8  836.28   293.6  839.99
#Mann= 3 , 0 , 0
       0      .1       0    78.3    .045       0    97.9     .06       0
Bank Sta=78.3,97.9
XS Rating Curve= 0 ,0
Exp/Cntr=0.3,0.1

Type RM Length L Ch R = 1 ,3062.8  ,31.9,33,34.1
XS GIS Cut Line= 2
     1576716.868      274060.591     1576513.822      274252.473
#Sta/Elev= 26
       0  849.97     9.6  845.78    19.3  841.28    28.9  836.68    38.5  831.57
    48.2  825.89    57.8  822.49    67.4  821.63    77.1  821.78    86.7  822.62
    96.3     824     106  825.13   115.6  825.56   125.2  825.56   134.9   825.1
   144.5  824.38   154.1  823.84   163.8  823.74   173.4  823.86     183   824.2
   192.7  825.12   202.3  826.39   211.9  828.02   221.6  830.22   240.8   834.1
   279.4     840
#Mann= 3 , 0 , 0
       0      .1       0    57.8    .045       0    86.7     .06       0
#XS Ineff= 2 , 0
                          120.82          830.57
Permanent Ineff=
       F       F
Bank Sta=57.8,86.7
XS Rating Curve= 0 ,0
Exp/Cntr=0.3,0.1

Type RM Length L Ch R = 1 ,3029.8  ,99.5,96.2,93
XS GIS Cut Line= 2
     1576717.932      274020.157      1576464.61      274237.014
#Sta/Elev= 25
       0  859.99      49   838.4    58.8  833.32    68.6  827.54    78.5  823.12
    88.3  821.52    98.1  821.36   107.9  821.73   117.7  822.88   127.5  824.44
   137.3  825.56   147.1  826.42   156.9   826.9   166.7  827.15   176.5  826.99
   196.2  825.76     206  825.38   215.8  825.77   225.6  826.92   274.6  834.46
   294.2  837.59     304   839.3   313.8  841.58   323.7  845.33   333.5     850
#Mann= 3 , 0 , 0
       0      .1       0    78.5    .045       0   107.9     .08       0
Bank Sta=78.5,107.9
XS Rating Curve= 0 ,0
Exp/Cntr=0.3,0.1

Type RM Length L Ch R = 1 ,2933.7  ,198.9,199.9,200.9
XS GIS Cut Line= 2
     1576643.062       273948.68     1576427.947      274192.033
#Sta/Elev= 29
       0     850     9.6  845.03    19.1  839.79    28.7  833.95    38.2  829.66
    47.8   826.4    66.9  822.24    76.4  820.42      86  819.43    95.5  819.24
   101.8  819.54   105.1   819.7   124.2  821.29   133.7  821.91   152.8  822.99
     172  823.91   191.1  824.97   210.2  826.27   229.3  827.96   238.8  828.91
   248.4  830.05   257.9  831.48   267.5  833.38     277  835.47   286.6  837.29
   296.1   838.9   305.7  841.54   315.2  845.35   324.8  849.99
#Mann= 3 , 0 , 0
       0     .08       0      86    .045       0   101.8     .06       0
Bank Sta=86,101.8
XS Rating Curve= 0 ,0
Exp/Cntr=0.3,0.1

Type RM Length L Ch R = 1 ,2733.7  ,263.3,264.1,264.9
XS GIS Cut Line= 2
     1576538.971      273775.895     1576266.023      274058.685
#Sta/Elev= 27
       0     880     9.8   875.4    19.6  870.59    29.5  865.59    39.3  860.45
    78.6  839.34    98.3  828.95   108.1  823.57   117.9  819.63   127.7   818.6
   137.6  819.23   139.4  819.51   157.2  822.12     167  823.19   176.9  824.09
   206.3  826.31   245.6  828.71   265.3     830   294.8  832.13   304.6  832.88
   314.4   833.8   324.2  835.33   334.1  837.91   343.9  841.02   353.7  844.43
   363.6   848.2     393     860
#Mann= 3 , 0 , 0
       0      .1       0   117.9    .045       0   139.4      .1       0
Bank Sta=117.9,139.4
XS Rating Curve= 0 ,0
Exp/Cntr=0.3,0.1

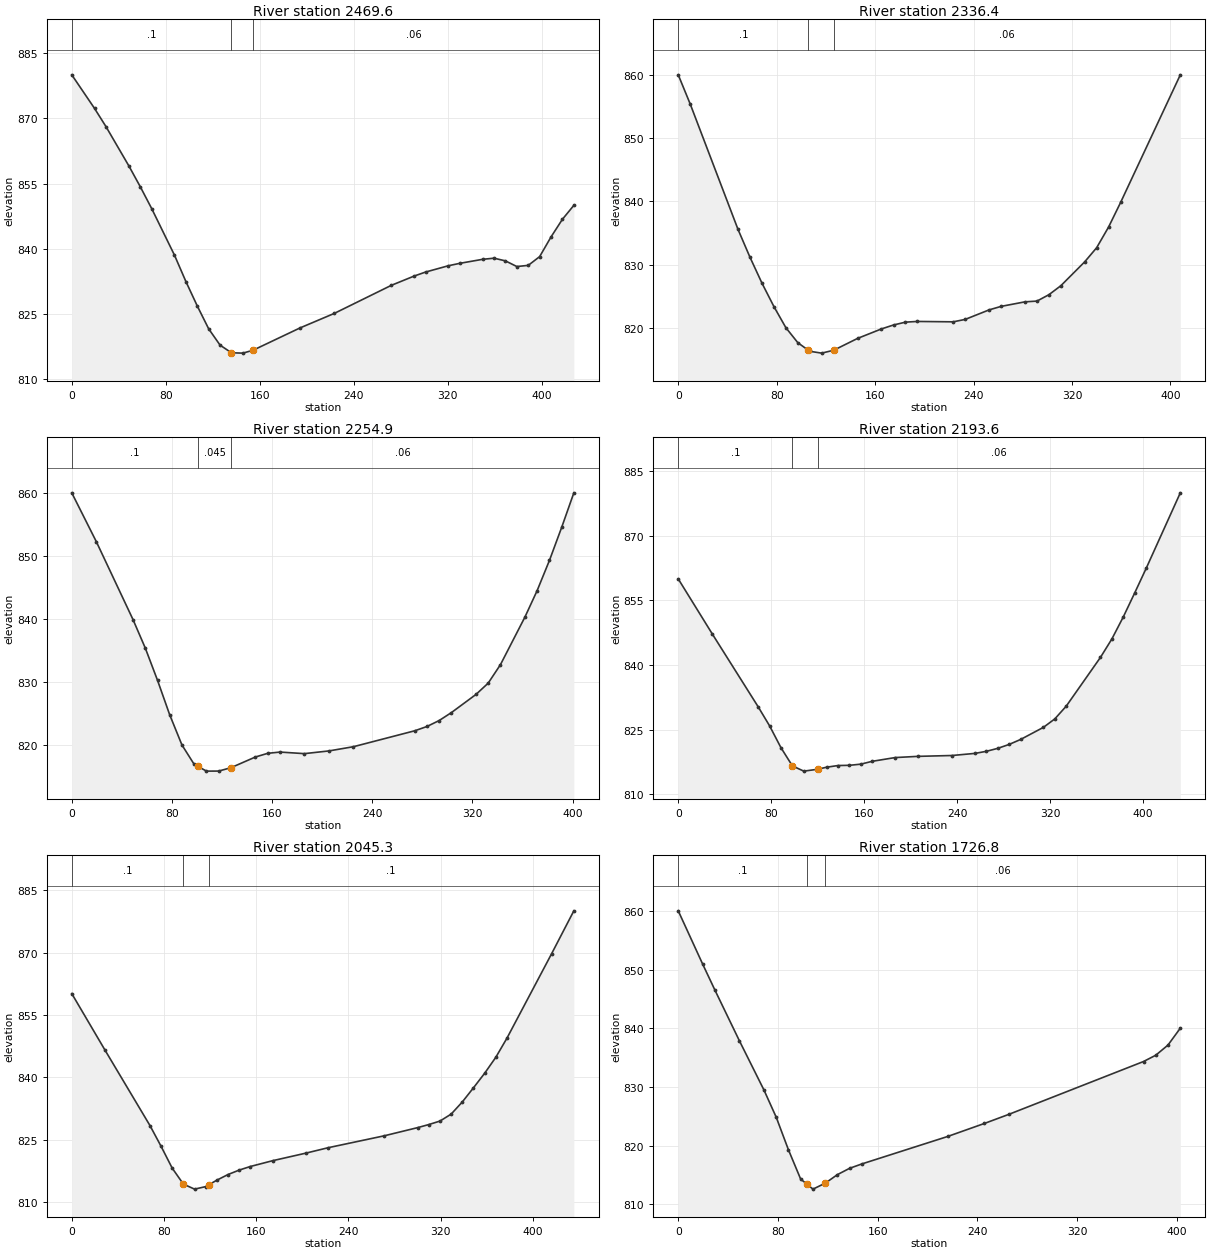
Type RM Length L Ch R = 1 ,2469.6  ,137.8,133.3,128.7
XS GIS Cut Line= 2
     1576346.501      273612.822     1576038.865       273909.31
#Sta/Elev= 30
       0     880    19.4  872.27    29.1   868.1    48.6  859.06    58.3  854.28
      68  849.26    87.4  838.55    97.1   832.5   106.8  826.87   116.5  821.62
   126.2  817.87   135.9  816.12   145.6  816.04   154.2   816.7   194.2  821.83
   223.3  825.16   271.9  831.62   291.3  833.75     301  834.67   320.4  836.12
   330.2  836.68   349.6   837.6   359.3  837.86     369  837.24   378.7  835.94
   388.4  836.21   398.1  838.22   407.8  842.75   417.5  846.81   427.2     850
#Mann= 3 , 0 , 0
       0      .1       0   135.9    .045       0   154.2     .06       0
Bank Sta=135.9,154.2
XS Rating Curve= 0 ,0
Exp/Cntr=0.3,0.1

Type RM Length L Ch R = 1 ,2336.4  ,82.8,81.4,80
XS GIS Cut Line= 3
     1576248.077      273555.991      1576168.55      273592.492
       1575986.2      273856.231
#Sta/Elev= 30
       0     860     9.7   855.4    48.6  835.55    58.3  831.16    68.1  827.04
    77.8  823.34    87.5  820.01    97.2  817.64   105.7  816.45   106.9  816.28
   116.6  815.99   126.4  816.45   145.8  818.32   165.2  819.82     175  820.44
   184.7  820.89   194.4     821   223.5  820.94   233.2  821.32   252.7  822.83
   262.4  823.38   281.8   824.1   291.6  824.22   301.3  825.23     311  826.65
   330.4  830.43   340.1  832.66   349.8  835.93   359.6  839.83   408.1     860
#Mann= 3 , 0 , 0
       0      .1       0   105.7    .045       0   126.4     .06       0
Bank Sta=105.7,126.4
XS Rating Curve= 0 ,0
Exp/Cntr=0.3,0.1

Type RM Length L Ch R = 1 ,2254.9  ,61.1,61.3,61.5
XS GIS Cut Line= 2
     1576149.653      273466.842     1575942.963      273810.514
#Sta/Elev= 30
       0     860    19.6  852.27    48.9  839.93    58.7  835.42    68.5   830.3
    78.2  824.85      88  820.06    97.8  816.98   100.8  816.66   107.6  815.92
   117.4  815.93   127.2  816.47   146.7  818.16   156.5  818.74   166.3  818.94
   185.8  818.69   205.4  819.12     225  819.79   273.9  822.31   283.7  822.99
   293.4  823.93   303.2  825.19   322.8  828.06   332.6  829.86   342.4  832.79
   361.9  840.31   371.7  844.52   381.5  849.29   391.3  854.54     401     860
#Mann= 3 , 0 , 0
       0      .1       0   100.8    .045       0   127.2     .06       0
Bank Sta=100.8,127.2
XS Rating Curve= 0 ,0
Exp/Cntr=0.3,0.1

Type RM Length L Ch R = 1 ,2193.6  ,148.9,148.3,147.7
XS GIS Cut Line= 2
     1576100.441       273431.93     1575874.066      273799.875
#Sta/Elev= 30
       0     860    29.4  847.17    68.7  830.32    78.6  825.86    88.4  820.78
    98.2  816.56     108  815.34     120  815.77   127.6  816.25   137.5  816.64
   147.3  816.69   157.1  816.96   166.9  817.62   186.6  818.49   206.2  818.77
   235.6  818.97   255.3  819.46   265.1  819.94   274.9  820.63   284.7  821.54
   294.6   822.7   314.2  825.51     324  827.47   333.8  830.42   363.3  841.77
   373.1  846.04   382.9  851.15   392.7  856.71   402.6  862.44     432     880
#Mann= 3 , 0 , 0
       0      .1       0    98.2    .045       0     120     .06       0
Bank Sta=98.2,120
XS Rating Curve= 0 ,0
Exp/Cntr=0.3,0.1

Type RM Length L Ch R = 1 ,2045.3  ,317.7,318.5,319.2
XS GIS Cut Line= 2
     1575969.318       273356.06     1575751.591      273733.256
#Sta/Elev= 28
       0  860.16      29  846.48    67.8  828.42    77.4  823.45    87.1  818.17
    96.8  814.32   106.5  813.11   116.1  813.71   118.7  814.13   125.8  815.26
   135.5  816.62   145.2  817.69   154.8  818.55   174.2  819.95   203.2  821.78
   222.6  823.09     271  825.94     300  827.91   309.7  828.65   319.4  829.49
   329.1  831.17   338.7  834.07   348.4  837.48   358.1  840.98   367.8  844.83
   377.5  849.45   416.2  869.75   435.5  880.08
#Mann= 3 , 0 , 0
       0      .1       0    96.8    .045       0   118.7      .1       0
Bank Sta=96.8,118.7
XS Rating Curve= 0 ,0
Exp/Cntr=0.3,0.1

Type RM Length L Ch R = 1 ,1726.8  ,190,191.7,193.3
XS GIS Cut Line= 2
     1575693.685      273203.875      1575481.33      273546.101
#Sta/Elev= 21
       0     860    19.6  850.92    29.5  846.46    49.1  837.84    68.8  829.45
    78.6  824.83    88.4  819.28    98.2  814.29     103  813.46   108.1  812.57
     118  813.59   127.7  815.04   137.5  816.12   147.4  816.87   216.1  821.54
   245.6  823.76   265.2  825.31   373.3  834.32   383.1  835.39   392.9  837.12
   402.8     840
#Mann= 3 , 0 , 0
       0      .1       0     103    .045       0     118     .06       0
Bank Sta=103,118
XS Rating Curve= 0 ,0
Exp/Cntr=0.3,0.1

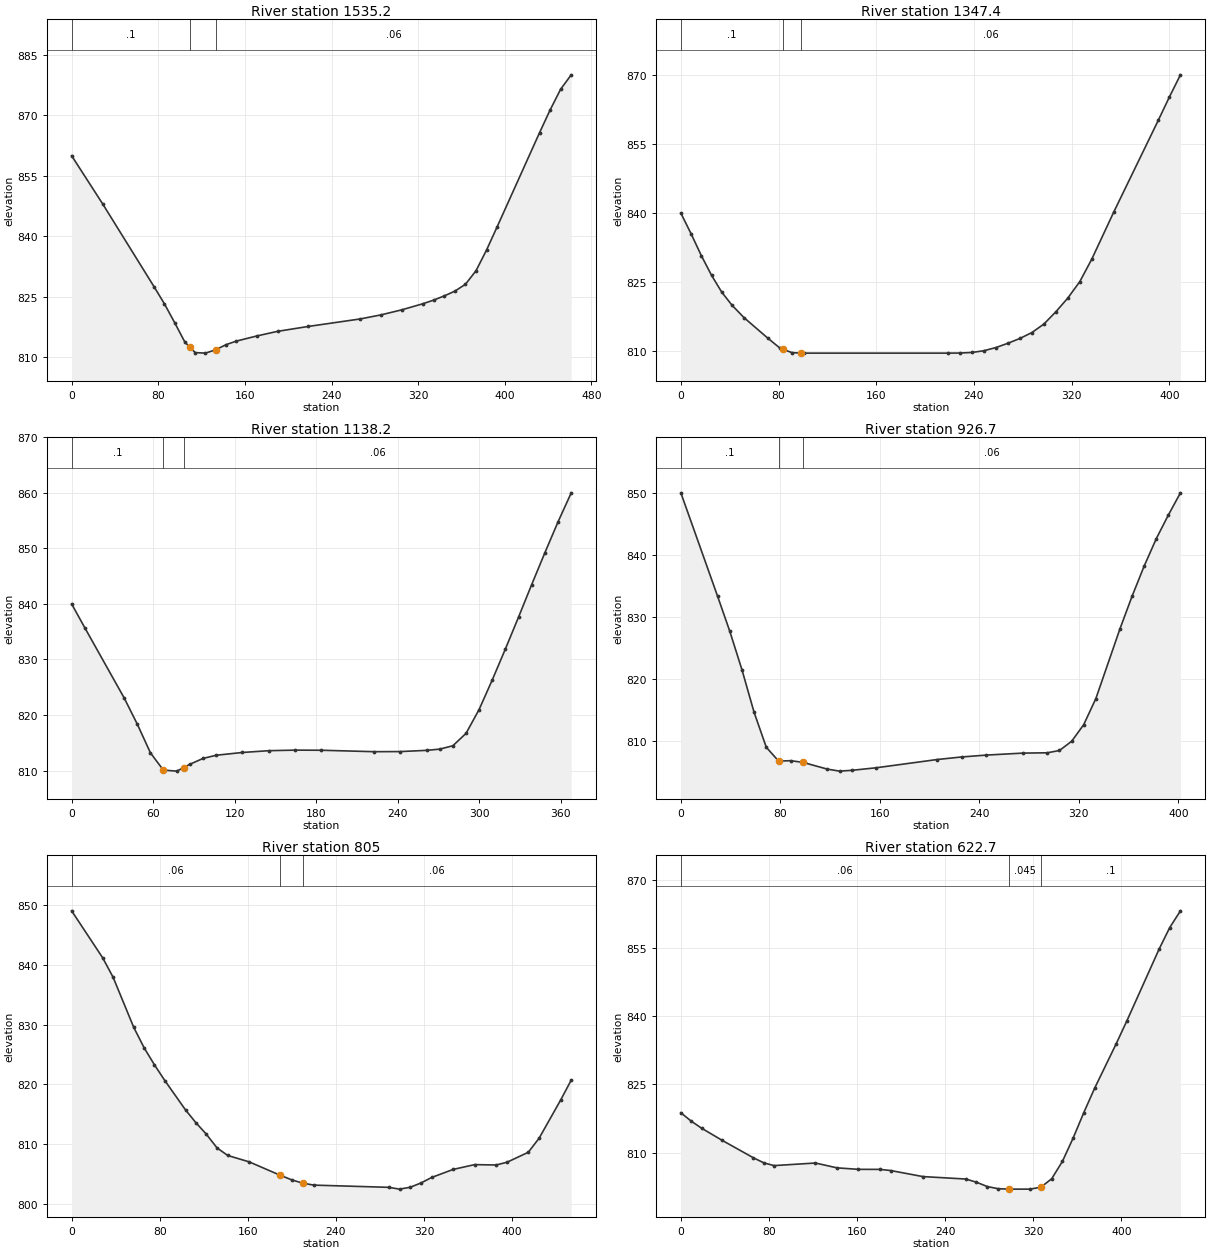
Type RM Length L Ch R = 1 ,1535.2  ,189.9,187.7,185.5
XS GIS Cut Line= 3
     1575545.824      273095.834      1575383.56      273318.766
     1575246.658      273444.212
#Sta/Elev= 30
       0  859.99    28.5  848.12    76.1  827.53    85.6  823.32    95.1  818.64
   104.6  813.78   109.4  812.47   114.1  811.19   123.6  811.06   133.1   811.9
   142.6  813.16   152.1  814.04   171.1  815.32   190.2  816.46   218.7  817.68
   266.2  819.52   285.5  820.53     305   821.8   324.6  823.32   334.4  824.21
   344.1  825.24   353.9  826.42   363.7  828.13   373.5   831.5   383.2  836.63
     393  842.39   432.1  865.68   441.9  871.34   451.6  876.48   461.4  880.05
#Mann= 3 , 0 , 0
       0      .1       0   109.4    .045       0   133.1     .06       0
Bank Sta=109.4,133.1
XS Rating Curve= 0 ,0
Exp/Cntr=0.3,0.1

Type RM Length L Ch R = 1 ,1347.4  ,212.4,209.3,206.2
XS GIS Cut Line= 4
     1575387.644      273007.954     1575354.351      273033.337
     1575204.783      273287.166     1575159.353      273343.863
#Sta/Elev= 30
       0     840     8.4   835.5    16.8  830.75    25.1  826.51    33.5  822.83
    41.9     820    51.7  817.31    71.3  812.83    81.2  810.68    83.4  810.46
      91   809.7    98.4  809.62   100.8   809.6   218.6   809.6   228.5  809.62
   238.3  809.74   248.1  810.12   257.9   810.8   267.7  811.73   277.6  812.78
   287.4  814.06   297.2  815.89     307  818.55   316.8  821.53   326.7  825.13
   336.5     830   354.6  840.28     391  860.16     400  865.17   409.1  870.01
#Mann= 3 , 0 , 0
       0      .1       0    83.4    .045       0    98.4     .06       0
Bank Sta=83.4,98.4
XS Rating Curve= 0 ,0
Exp/Cntr=0.3,0.1

Type RM Length L Ch R = 1 ,1138.2  ,212.2,211.4,210.6
XS GIS Cut Line= 2
     1575175.256      272910.865     1575033.224      273249.869
#Sta/Elev= 29
       0     840     9.7   835.7    38.7  823.05    48.4  818.31      58  813.18
    67.5  810.08    77.4   809.9    82.5  810.55      87  811.13    96.7  812.19
   106.4  812.76   125.7  813.26   145.1  813.58   164.4  813.68   183.8  813.66
   222.5   813.4   241.8  813.42   261.2  813.64   270.8  813.86   280.5  814.47
   290.2   816.7   299.8  820.99   309.5  826.32   319.2  831.92   328.9  837.67
   338.5  843.48   348.2  849.21   357.9  854.78   367.6     860
#Mann= 3 , 0 , 0
       0      .1       0    67.5    .045       0    82.5     .06       0
Bank Sta=67.5,82.5
XS Rating Curve= 0 ,0
Exp/Cntr=0.3,0.1

Type RM Length L Ch R = 1 ,926.7   ,116.6,121.7,227.8
XS GIS Cut Line= 3
     1574998.093      272814.595     1574898.974       273112.77
      1574895.23      273200.173
#Sta/Elev= 28
       0     850    29.5  833.38    39.3  827.75    49.1  821.55    58.9  814.67
    68.7  809.05    78.6  806.83    88.4  806.89    98.2  806.62   117.8  805.53
   127.6  805.21   137.5  805.34   157.1  805.75   206.2  807.08   225.8  807.49
   245.5  807.79   274.9  808.11   294.6  808.16   304.4  808.53   314.2  810.01
   323.9  812.68   333.7  816.89   353.1  828.13   362.8  833.35   372.5   838.2
   382.3  842.63     392  846.43   401.7     850
#Mann= 3 , 0 , 0
       0      .1       0    78.6    .045       0    98.2     .06       0
Bank Sta=78.6,98.2
XS Rating Curve= 0 ,0
Exp/Cntr=0.3,0.1

Type RM Length L Ch R = 1 ,805     ,184.6,182.3,78
XS GIS Cut Line= 3
     1574840.266      272730.984     1574886.473      272844.155
     1574801.666       273164.52
#Sta/Elev= 30
       0  848.98    28.2  841.13    37.6  837.91    56.4  829.52    65.8  826.12
    75.2  823.27    84.6  820.65   103.4  815.75   112.8  813.62   122.2  811.72
     132  809.41   141.7  808.15   161.2  807.08   188.9  804.88   200.2  804.05
     210  803.53   219.7   803.2   287.9  802.83   297.7  802.53   307.4  802.84
   317.2  803.56   326.9  804.48   346.4  805.82   365.9  806.62   385.4  806.56
   395.2  807.01   414.6  808.68   424.4  811.02   443.9  817.37   453.6  820.73
#Mann= 3 , 0 , 0
       0     .06       0   188.9    .045       0     210     .06       0
Bank Sta=188.9,210
XS Rating Curve= 0 ,0
Exp/Cntr=0.3,0.1

Type RM Length L Ch R = 1 ,622.7   ,134.6,132.8,131.1
XS GIS Cut Line= 3
     1574766.723      272749.723      1574812.93      272862.894
     1574728.124      273183.259
#Sta/Elev= 30
       0  818.77     9.4  816.93    18.8  815.38    37.6  812.69    65.8  808.88
    75.2  807.77    84.6  807.15   122.2  807.72   141.7  806.66   161.2  806.33
   180.7  806.32   190.5  806.07   219.7  804.74   258.7   804.2   268.4   803.5
   278.2  802.55   287.9  802.08   297.7  801.98   317.2  801.98   326.9  802.41
   336.7  804.26   346.4  808.06   356.2  813.22   365.9  818.82   375.7  824.17
   395.2   833.9   404.9  838.94   434.2  854.73   443.9  859.49   453.6  863.16
#Mann= 3 , 0 , 0
       0     .06       0   297.7    .045       0   326.9      .1       0
Bank Sta=297.7,326.9
XS Rating Curve= 0 ,0
Exp/Cntr=0.3,0.1

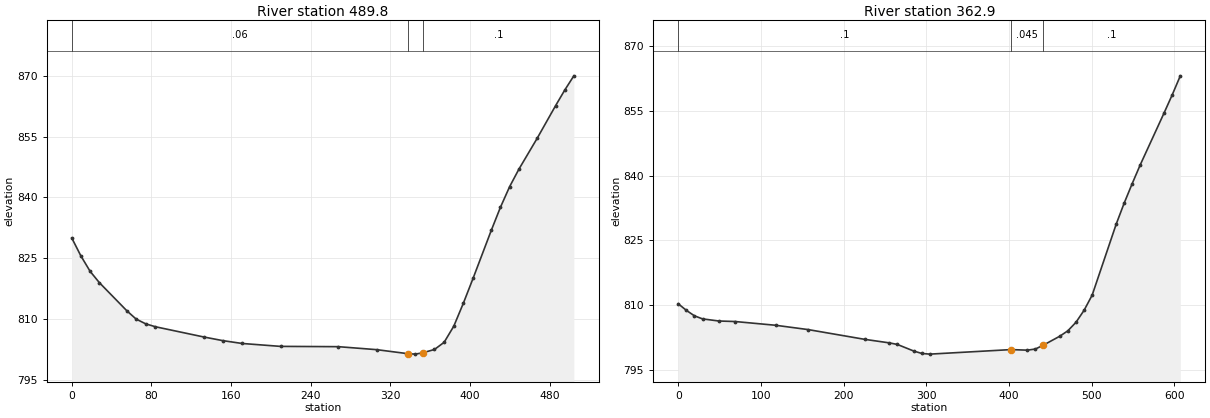
Type RM Length L Ch R = 1 ,489.8   ,125.1,126.9,128.6
XS GIS Cut Line= 4
     1574754.467      272708.537     1574707.497      272753.073
     1574621.026      273080.191     1574633.669      273180.718
#Sta/Elev= 30
       0     830     9.2  825.56    18.5  821.75    27.7  818.99    55.5     812
    64.7  809.99    74.4  808.81    84.1   808.1   132.4  805.59   151.7  804.68
   171.1  803.98   209.7  803.26   267.7  803.19   306.4  802.45   337.7  801.46
   345.1  801.35   352.7  801.68   364.4   802.5   374.1  804.27   383.8  808.25
   393.4  813.91   403.1  820.01   421.5  831.91   430.7   837.6   439.9  842.67
   449.1  846.93   467.6  854.61     486  862.61   495.2  866.46   504.4     870
#Mann= 3 , 0 , 0
       0     .06       0   337.7    .045       0   352.7      .1       0
Bank Sta=337.7,352.7
XS Rating Curve= 0 ,0
Exp/Cntr=0.3,0.1

Type RM Length L Ch R = 1 ,362.9   ,350,362.9,369.8
XS GIS Cut Line= 3
      1574651.12      272622.699     1574493.567      273097.959
      1574539.14      273194.313
#Sta/Elev= 30
       0  810.29     9.8  808.76    19.6  807.49    29.4  806.78    49.1  806.29
    68.7  806.17   117.8   805.3   157.1   804.3   225.8  802.03   255.3  801.22
   265.1  800.85   284.7  799.34   294.5  798.77   304.3  798.61   402.5  799.66
   422.2  799.53     432  799.79   441.8  800.71   461.4  802.75   471.2  804.01
   481.1  805.99   490.9  808.77   500.7   812.3   529.8  828.77   539.4  833.62
   549.1  838.14   558.8  842.48   587.9  854.62   597.6  858.76   607.3  863.13
#Mann= 3 , 0 , 0
       0      .1       0   402.5    .045       0   441.8      .1       0
Bank Sta=402.5,441.8
XS Rating Curve= 0 ,0
Exp/Cntr=0.3,0.1

Chan Stop Cuts=-1
Use User Specified Reach Order=0
Composite Channel Slope=5